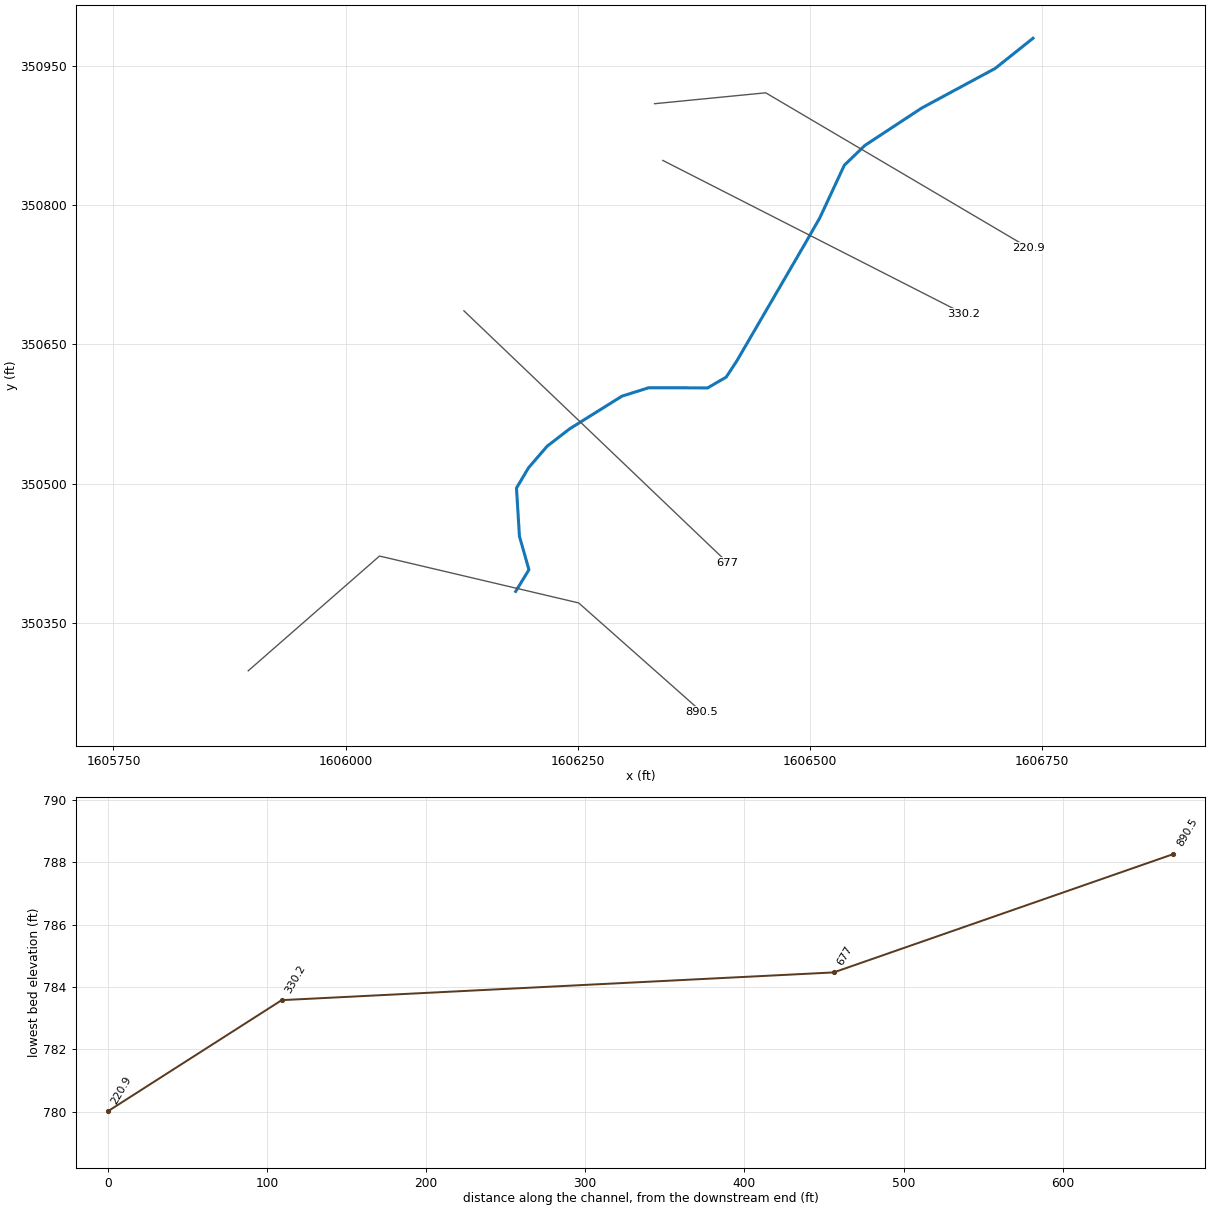
--- stfrktwl2.prj (project) ---

Proj Title=stfrktwl2
Current Plan=p01
Default Exp/Contr=0,0
English Units
Geom File=g01
Flow File=f01
Plan File=p01
BEGIN DESCRIPTION:
END DESCRIPTION:
DSS Export Rating Curves= 0
DSS Export Rating Curve Sorted= 0
DSS Export Volume Flow Curves= 0
DXF OffsetX= 0
DXF OffsetY= 0
DXF ScaleX= 0
DXF ScaleY= 0

--- stfrktwl2.p01 (plan) ---

Plan Title=Approximate Study - 100yr
Program Version=4.00
Geom File=g01
Flow File=f01
Subcritical Flow
K Sum by GR= 0
Std Step Tol= 0.01
Critical Tol= 0.01
Num of Std Step Trials= 20
Max Error Tol= 0.3
Flow Tol Ratio= 0.001
Split Flow NTrial= 30
Split Flow Tol= 0.02
Split Flow Ratio= 0.02
Log Output Level= 0
Friction Slope Method= 1
Unsteady Friction Slope Method= 2
Unsteady Bridges Friction Slope Method= 1
Parabolic Critical Depth
Global Vel Dist= 0 , 0 , 0
Global Log Level= 0
CheckData=True
Encroach Param=-1 ,0,0, 0
Run HTab= 0
Run UNet= 0
Run PostProcess= 0
Run WQNet= 0
UNET Theta= 0
UNET Theta Warmup= 0
UNET ZTol= 0
UNET ZSATol= 0
UNET MxIter= 0
UNET MaxInSteps= 0
UNET DtIC= 0
UNET DtMin= 0
UNET MaxCRTS= 0
UNET WFStab= 0
UNET SFStab= 0
UNET WFX= 1
UNET SFX= 1
UNET DSS MLevel= 1
UNET DZMax Abort= 0
UNET Convert EG Bridges= 0
UNET Use Existing IB Tables= 0
UNET Froude Reduction=False
UNET Froude Limit= 0
UNET Froude Power= 0
UNET Time Slicing=0,0, 5
Write IC File= 0
Echo Input=False
Echo Output=False
Write Detailed= 0
Detailed Automatic Start=False, 0
WQ ULTIMATE=-1
WQ Max Comp Step=1HOUR
WQ Output Interval=15MIN
WQ Output Selected Increments= 0
WQ Output face flow=0
WQ Output face velocity=0
WQ Output face area=0
WQ Output face dispersion=0
WQ Output cell volume=0
WQ Output cell surface area=0
WQ Output cell continuity=0
WQ Output face conc=0
WQ Output face dconc_dx=0
WQ Output face courant=0
WQ Output face peclet=0
WQ Output face adv mass=0
WQ Output face disp mass=0
WQ Output cell mass=0
WQ Output cell source sink temp=0
WQ Output cell source sink nsm=0
WQ Output MaxMinRange=-1
WQ Daily Max Min Mean=-1
WQ Daily Range=0
WQ Daily Time=0
WQ Create Restart=0
WQ Fixed Restart=0
WQ System Summary=False
Sorting and Armoring Iterations= 10
XS Update Threshold= 0.02
Hydraulics Update Threshold= 0.02
Energy Slope Method= 1
Volume Change Method= 0
XS Weighting Method= 0
Number of US Weighted Cross Sections= 1
Number of DS Weighted Cross Sections= 1
Upstream XS Weight=0.25
Main XS Weight=0.5
Downstream XS Weight=0.25
Number of DS XS's Weighted with US Boundary= 1
Upstream Boundary Weight= 1
Weight of XSs Associated with US Boundary= 0
Number of US XS's Weighted with DS Boundary= 1
Downstream Boundary Weight= 0.5
Weight of XSs Associated with DS Boundary= 0.5
Sediment Output Level= 4
Mass or Volume Output= 0
Output Increment Type= 1
Profile and TS Output Increment= 10
XS Output Flag= 0
XS Output Increment= 10
Disregard all LS=0
Disregard all Conn=0
Disregard all Breaches=0
Disregard all Pumps=0

--- stfrktwl2.f01 (steady flow) ---

Flow Title=USGS Regression Equation
Program Version=4.00
Number of Profiles= 1
Profile Names=P100yr
River Rch & RM=stfrktwl2,Main            ,890.5
     303
River Rch & RM=stfrktwl2,Main            ,677
     512
River Rch & RM=stfrktwl2,Main            ,220.9
     517
Boundary for River Rch & Prof#=stfrktwl2,Main            , 1
Up Type= 0
Dn Type= 3
Dn Slope=0.017654
DSS Import GetInterval= 0
DSS Import GetPeak= 0
DSS Import FillOption= 0

--- stfrktwl2.g01 (geometry) ---

Geom Title=USGS 3m DEM
Program Version=4.00

River Reach=stfrktwl2       ,Main
Reach XY= 20
     1606183.267      350384.221     1606197.505      350407.532
      1606187.31      350443.506     1606184.099       350495.44
     1606197.059      350517.242     1606217.096      350540.474
      1606241.52      350559.312     1606297.633       350594.36
     1606326.349      350603.385     1606364.911      350603.385
     1606389.882      350603.209     1606410.004      350614.902
     1606421.405      350632.269     1606494.104      350757.165
     1606510.987      350786.667      1606537.21      350842.963
     1606559.363      350864.295     1606620.665      350904.592
     1606699.692      350947.171     1606740.465      350979.658

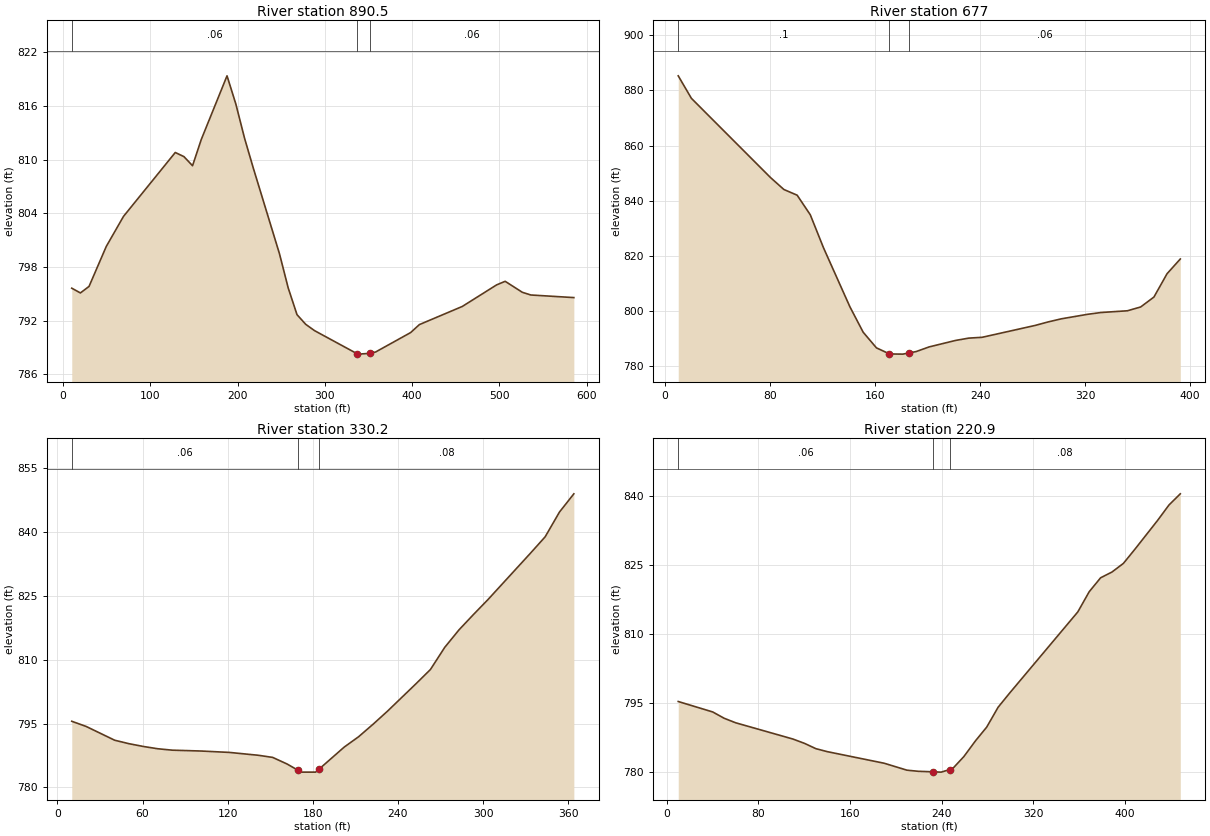
Type RM Length L Ch R = 1 ,890.5   ,224.9,213.5,202.1
XS GIS Cut Line= 4
      1605895.13        350298.7      1606036.58      350422.285
     1606251.086      350371.805       1606383.6      350254.473
#Sta/Elev= 30
     9.9  795.64    19.8  795.11    29.7  795.84    49.4   800.3    69.2  803.67
   128.5  810.81   138.4  810.35   148.3  809.33   158.2  812.24   187.8  819.38
   197.9  816.23   207.9   812.4   217.9  809.07   247.9  799.49   257.9  795.67
     268  792.68     278   791.6     288   790.9   336.6 788.328   338.1  788.27
   351.6 788.354   358.1  788.51   398.2  790.68   408.2  791.57   457.4   793.6
   496.7  796.01   506.5  796.41   526.2  795.18     536  794.88   585.2  794.59
#Mann= 3 , 0 , 0
     9.9     .06       0   336.6    .045       0   351.6     .06       0
Bank Sta=336.6,351.6
XS Rating Curve= 0 ,0
Exp/Cntr=0.3,0.1

Type RM Length L Ch R = 1 ,677     ,340,346.8,353.6
XS GIS Cut Line= 2
     1606127.483      350686.249     1606411.471       350415.17
#Sta/Elev= 30
    10.1  885.26    20.1  877.13    30.2  872.31    80.5  848.37    90.6  844.09
   100.7  842.03   110.7  834.94   120.8  822.95   140.9   801.6     151   792.4
   161.1  786.74   170.7 784.618   171.1  784.53   181.2  784.47   185.7 784.878
   191.3  785.39   201.3  787.09   221.5  789.44   231.5  790.27   241.6  790.56
   281.9  794.85   291.9  796.13     302  797.26   322.1   798.9   332.2  799.54
   352.3  800.17   362.4  801.55   372.5  805.14   382.5  813.59   392.6  818.93
#Mann= 3 , 0 , 0
    10.1      .1       0   170.7    .045       0   185.7     .06       0
Bank Sta=170.7,185.7
XS Rating Curve= 0 ,0
Exp/Cntr=0.3,0.1

Type RM Length L Ch R = 1 ,330.2   ,110.6,109.3,108.2
XS GIS Cut Line= 2
     1606341.729       350848.16     1606666.076      350682.964
#Sta/Elev= 30
    10.1  795.53    20.2  794.32    40.4  791.07    50.6  790.25    60.7   789.6
    70.8  789.07    80.9  788.74   101.1  788.54   121.3  788.21   141.6  787.54
   151.7  787.04   161.8   785.5   169.4 784.057   171.9  783.58     182  783.58
   184.4 784.281   202.2  789.48   212.3   791.9   222.4  794.81   232.6  797.89
   252.8  804.37   262.9  807.69     273   812.9   283.1  817.03   293.2   820.6
   303.3  824.07   333.7  835.13   343.8  838.89   353.9  844.71     364  848.98
#Mann= 3 , 0 , 0
    10.1     .06       0   169.4    .045       0   184.4     .08       0
Bank Sta=169.4,184.4
XS Rating Curve= 0 ,0
Exp/Cntr=0.3,0.1

Type RM Length L Ch R = 1 ,220.9   ,229.3,220.9,212.3
XS GIS Cut Line= 3
     1606332.846      350909.215     1606452.544       350920.95
     1606735.358      350754.312
#Sta/Elev= 29
      10  795.36    40.1  793.09    50.1  791.72    60.1  790.74   110.2   787.2
   120.3  786.26   130.2  785.11   140.2  784.46   189.9  781.94   209.8  780.43
   219.7  780.19   232.1  780.08   239.6  780.01   247.1  780.56   249.6  780.75
   259.5   783.4   269.5  786.78   279.4  789.79   289.4  794.12   299.3  797.15
     359  814.84   368.9  819.21   378.9  822.25   388.8   823.5   398.8  825.38
   408.7  828.41   428.6   834.7   438.6  838.07   448.5   840.5
#Mann= 3 , 0 , 0
      10     .06       0   232.1    .045       0   247.1     .08       0
Bank Sta=232.1,247.1
XS Rating Curve= 0 ,0
Exp/Cntr=0.3,0.1

Chan Stop Cuts=-1
Use User Specified Reach Order=0